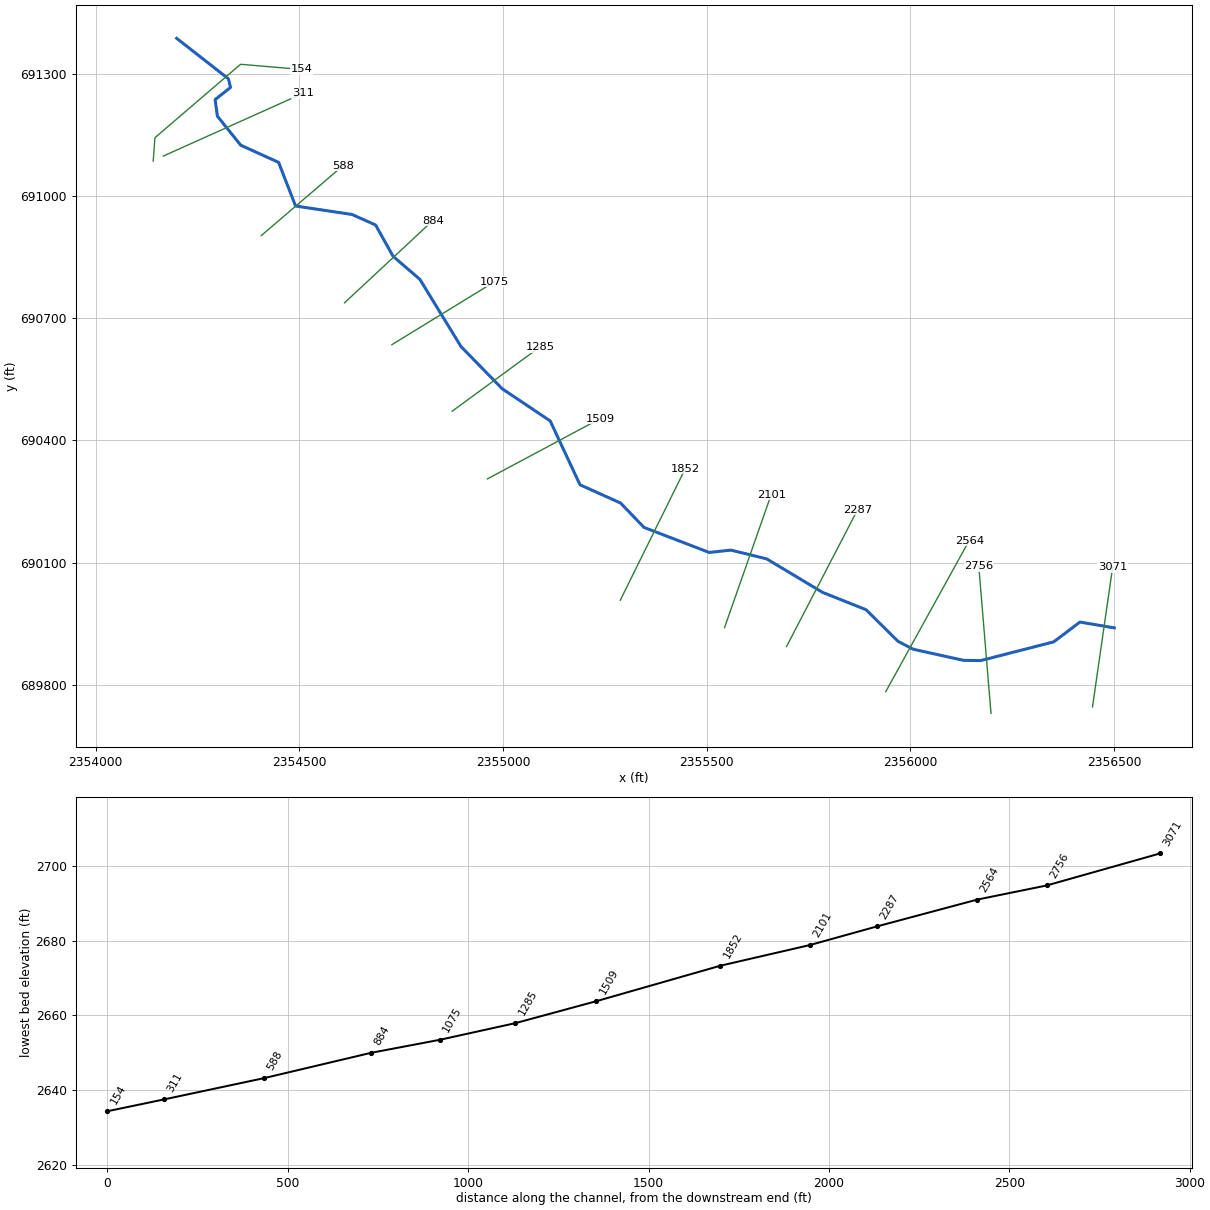
--- NCHLSLNRN.prj (project) ---

Proj Title=NCHLSLNRN
Current Plan=p01
Default Exp/Contr=0,0
English Units
Geom File=g01
Flow File=f01
Plan File=p01
BEGIN DESCRIPTION:
----------MODEL BY WOOD PLC 2022----------
AFH study
Randolph County, WV
HEC-RAS Version: RAS 6.2
Vertical Datum: NAVD88
Projection: NAD 1983 StatePlane West Virginia S FIPS 4702 (US Feet)
Terrain: 1-meter LIDAR (FEMA Region III 3DEP collected 2016-2018)
Land Use: 2019 NLCD
Hydrologic Method:
WV SIR2010-5033 regression equations
Additional Model Notes:
None
END DESCRIPTION:
DSS Export Rating Curves= 0
DSS Export Rating Curve Sorted= 0
DSS Export Volume Flow Curves= 0
DXF OffsetX= 0
DXF OffsetY= 0
DXF ScaleX= 0
DXF ScaleY= 0

--- NCHLSLNRN.p01 (plan) ---

Plan Title=Floodplain
Program Version=6.20
Short Identifier=Floodplain
Geom File=g01
Flow File=f01
Subcritical Flow
K Sum by GR= 0
Std Step Tol= 0.01
Critical Tol= 0.01
Num of Std Step Trials= 20
Max Error Tol= 0.3
Flow Tol Ratio= 0.001
Split Flow NTrial= 30
Split Flow Tol= 0.02
Split Flow Ratio= 0.02
Log Output Level= 0
Friction Slope Method= 1
Unsteady Friction Slope Method= 2
Unsteady Bridges Friction Slope Method= 1
Parabolic Critical Depth
Global Vel Dist= 0 , 0 , 0
Global Log Level= 0
CheckData=True
Encroach Param=-1 ,0,0, 0
Mapping Interval=1HOUR
Computation Time Step Use Courant=        0
Computation Time Step Use Time Series=    0
Computation Time Step Count To Double=0
Computation Time Step Max Doubling=0
Computation Time Step Max Halving=0
Computation Time Step Residence Courant=0
Run HTab= 0
Run UNet= 0
Run Sediment= 0
Run PostProcess= 0
Run WQNet= 0
Run RASMapper=-1
UNET Theta= 0
UNET Theta Warmup= 0
UNET ZTol= 0
UNET ZSATol= 0
UNET MxIter= 0
UNET Max Iter WO Improvement= 0
UNET MaxInSteps= 0
UNET DtIC= 0
UNET DtMin= 0
UNET MaxCRTS= 0
UNET WFStab= 0
UNET SFStab= 0
UNET WFX= 1
UNET SFX= 1
UNET Gravity=32.174
UNET 1D Methodology=Finite Difference
UNET DSS MLevel= 1
UNET Pardiso=0
UNET DZMax Abort= 0
UNET Use Existing IB Tables= 0
UNET Froude Reduction=False
UNET Froude Limit= 0
UNET Froude Power= 0
UNET D1 Cores= 0
UNET WindReference=Eulerian
UNET WindDragFormulation=Hsu (1988)
UNET D2 Coriolis=0
UNET D2 Cores= 0
UNET D2 Theta= 1
UNET D2 Theta Warmup= 1
UNET D2 Z Tol= 0.01
UNET D2 Volume Tol= 0.01
UNET D2 Max Iterations= 20
UNET D2 Equation= 0
UNET D2 RampUpFraction=0.1
UNET D2 TimeSlices= 1
UNET D2 Turbulence Formulation=Non-Conservative (original)
UNET D2 Eddy Viscosity=0.3
UNET D2 Transverse Eddy Viscosity=0.1
UNET D2 Smagorinsky Mixing=0
UNET D2 BCVolumeCheck=0
UNET D2 Cores=0
UNET D2 SolverType=PARDISO (Direct)
UNET D2 Minimum Iterations= 2147483647
UNET D2 Maximum Iterations= 2147483647
UNET D2 Restart Number= 10
UNET D2 Relaxation Coeff=1.3
UNET D2 SOR Precondition Iterations= 10
UNET D2 ILUT Maximum Fill= 8
UNET D2 ILUT Tolerance=1E-08
UNET D1D2 MaxIter= 0
UNET D1D2 ZTol=0.01
UNET D1D2 QTol=0.1
UNET D1D2 MinQTol=1
Write IC File= 0
Write IC File at Fixed DateTime=0
Write IC File at Sim End=0
Echo Input=False
Echo Parameters=False
Echo Output=False
Write Detailed= 0
HDF Write Warmup=0
HDF Write Time Slices=0
HDF Flush=0
HDF Compression= 1
HDF Chunk Size= 1
HDF Spatial Parts= 1
HDF Use Max Rows=0
HDF Fixed Rows= 1
Calibration Method= 0
Calibration Iterations= 20
Calibration Max Change=0.05
Calibration Tolerance=0.2
Calibration Maximum=1.5
Calibration Minimum=0.5
Calibration Optimization Method= 1
WQ AD Non Conservative
WQ ULTIMATE=-1
WQ Max Comp Step=1HOUR
WQ Output Interval=15MIN
WQ Output Selected Increments= 0
WQ Output face flow=0
WQ Output face velocity=0
WQ Output face area=0
WQ Output face dispersion=0
WQ Output cell volume=0
WQ Output cell surface area=0
WQ Output cell continuity=0
WQ Output cumulative cell continuity=0
WQ Output face conc=0
WQ Output face dconc_dx=0
WQ Output face courant=0
WQ Output face peclet=0
WQ Output face adv mass=0
WQ Output face disp mass=0
WQ Output cell mass=0
WQ Output cell source sink temp=0
WQ Output nsm pathways=0
WQ Output nsm derived pathways=0
WQ Create Restart=0
WQ Fixed Restart=0
WQ System Summary=0
WQ Write To DSS=0
Sorting and Armoring Iterations= 10
XS Update Threshold= 0.02
Bed Roughness Predictor= 0
Hydraulics Update Threshold= 0.02
Energy Slope Method= 1
Volume Change Method= 1
Sediment Retention Method= 0
Sediment TS Multiplier= 1
Warm Up Method= 0
XS Weighting Method= 0
Number of US Weighted Cross Sections= 1
Number of DS Weighted Cross Sections= 1
Upstream XS Weight=0
Main XS Weight=1
Downstream XS Weight=0
Number of DS XS's Weighted with US Boundary= 1
Upstream Boundary Weight= 1
Weight of XSs Associated with US Boundary= 0
Number of US XS's Weighted with DS Boundary= 1
Downstream Boundary Weight= 0.5
Weight of XSs Associated with DS Boundary= 0.5
Percentile Method= 0
Sediment Output Level= 3
Mass or Volume Output= 0
Output Increment Type= 1
Profile and TS Output Increment= 1
Transport Output Increment 1
XS Output Flag= 0
XS Output Increment= 10
Read HDF5 Sediment Hotstart= 0
Sediment Hotstart Type= 0
Write Gradation File= 0
Read Gradation Hotstart= 0
Write HDF5 File= 1
Write Binary Output= 1
Write DSS Sediment File= 0
DSS Sediment Output Type= 1
SV Curve= 0
Specific Gage Flag= 0
Subcell Erosion Methods= 0
Subcell Deposition Methods= 0
Advection Scheme= 1
Matrix Solver= 0
Implicit Weighting Factor= 1
Maximum Outer Loop Convergence Iterations= 5
Convergence Maximum Absolute= 0.001
Convergence RMSE= 0.0001
Grain Fractions Max Abs Error= 0.001
Max Subgrid Regions= 1
Max Subgrid Length Scale= 3.402823E+38
Initial Layer Thickness= 3.402823E+38
Min Layer Thickness= 3.402823E+38
Max Layer Thickness= 3.402823E+38
Number of Layers= 5

--- NCHLSLNRN.f01 (steady flow) ---

Flow Title=Flow
Program Version=6.20
Number of Profiles= 1
Profile Names=P100yr
River Rch & RM=NCHLSLNRN,Main            ,3071
     455
Boundary for River Rch & Prof#=NCHLSLNRN,Main            , 1
Up Type= 0
Dn Type= 3
Dn Slope=0.02039
DSS Import GetInterval= 0
DSS Import GetPeak= 0
DSS Import FillOption= 0

--- NCHLSLNRN.g01 (geometry) ---

Geom Title=Geometry
Program Version=6.20

River Reach=NCHLSLNRN       ,Main
Reach XY= 30
     2356501.095      689939.451     2356416.622      689953.773
      2356352.32      689905.155     2356173.046      689859.206
     2356131.191      689859.688      2356007.42      689887.034
      2355970.18      689906.305      2355891.44      689984.188
     2355784.677      690026.7052355647.49806709690108.957492651
2355559.71844881690130.4923239012355506.35341751690124.737271506
     2355346.342      690186.251     2355288.726      690246.122
     2355189.191      690290.941     2355115.927      690447.885
     2354998.216      690526.693     2354897.177      690630.177
2354796.02212721 690795.44148704 2354730.1213733690852.193876887
     2354687.369      690928.847     2354629.671      690954.743
     2354490.782      690975.576     2354449.115      691082.781
     2354356.233      691124.882     2354298.942      691196.062
       2354293.3      691236.861      2354331.06      691266.809
     2354325.852      691288.076     2354198.911      691387.375

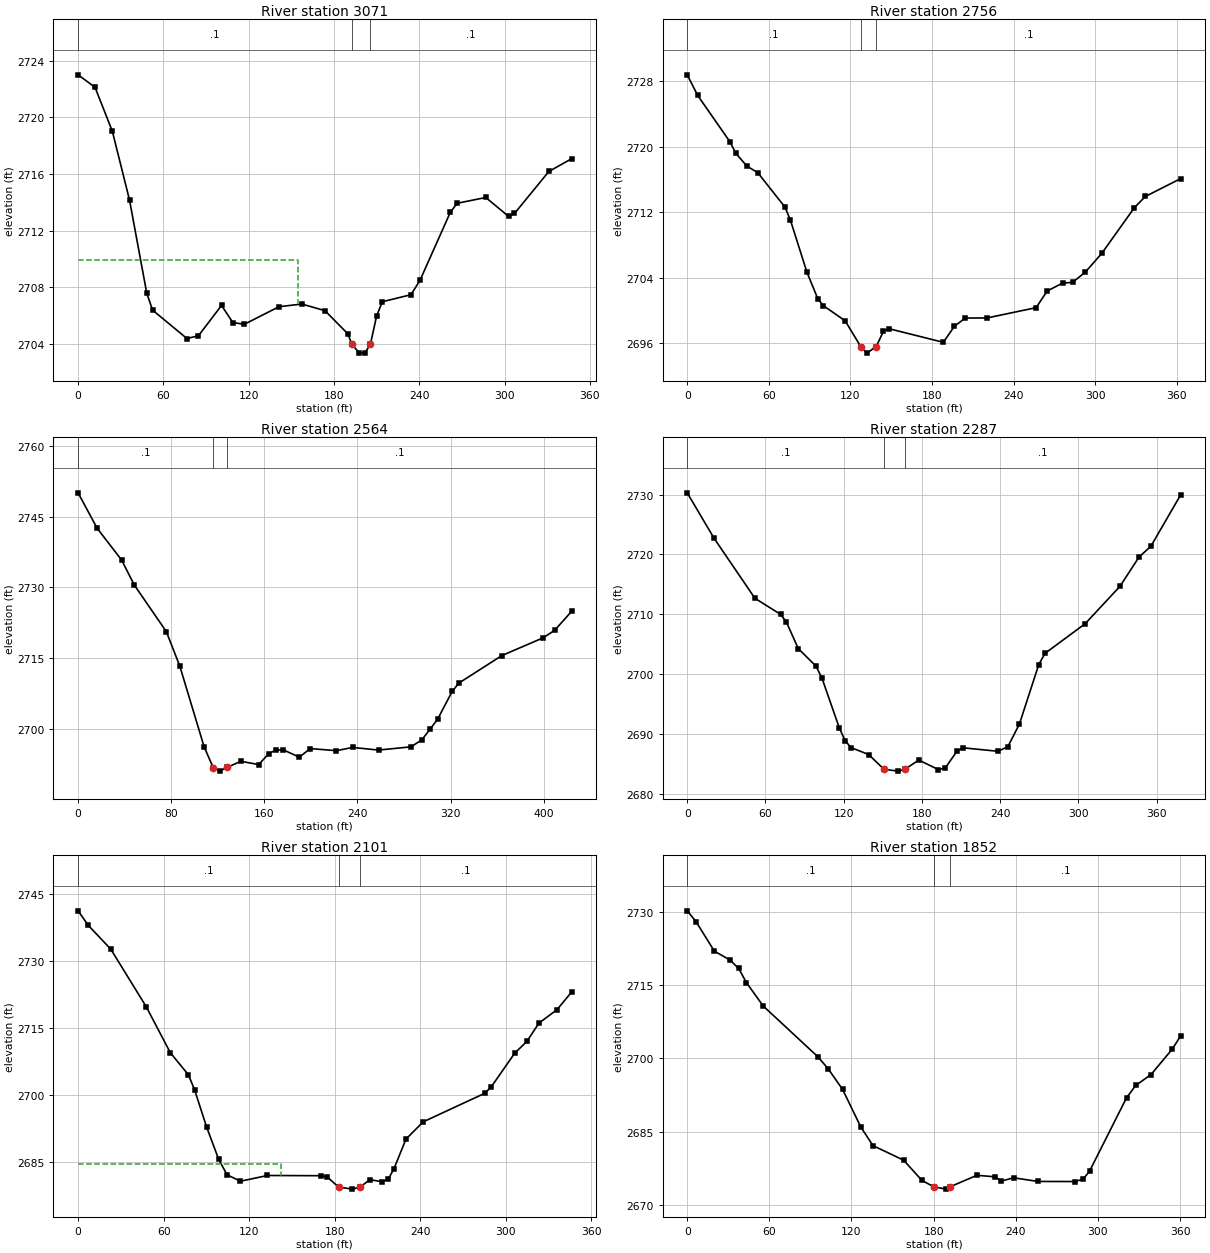
Type RM Length L Ch R = 1 ,3071    ,311.9,314.9,315.4
XS GIS Cut Line= 2
2356447.48353398 689745.354042622356497.04496289690088.979949709
#Sta/Elev= 30
       0 2723.01    11.9 2722.13    24.1 2719.02    36.2 2714.15    48.3 2707.58
    52.4 2706.38    76.6 2704.37    84.7 2704.57   100.9 2706.71   108.9  2705.5
     117 2705.38   141.3 2706.62   157.4 2706.81   173.7 2706.34   189.8  2704.7
   192.6 2703.97   197.9 2703.34   201.9 2703.36  205.67 2703.98     210 2705.96
     214 2706.97   234.2 2707.47   240.6  2708.5   261.8 2713.28   266.6 2713.93
   286.8 2714.34   302.9    2713     307 2713.21   331.2 2716.18   347.2 2717.08
#Mann= 3 ,-1,0
       0      .1       0   192.6    .045       0  205.67      .1       0
#XS Ineff= 2 , 0
           154.8 2709.89
Permanent Ineff=
       F       F
Bank Sta=192.6,205.67
XS Rating Curve= 0 ,0
Exp/Cntr(USF)=0,0
Exp/Cntr=0.3,0.1

Type RM Length L Ch R = 1 ,2756    ,195.9,192.1,189.1
XS GIS Cut Line= 2
2356198.29502181689729.521849948 2356168.2820677 690091.07535278
#Sta/Elev= 30
       0 2728.78     7.7 2726.26    31.3 2720.62    35.8 2719.18    43.8 2717.63
    51.8 2716.83    71.9  2712.6    75.9    2711      88 2704.65      96 2701.41
     100 2700.57   116.1 2698.71  127.56 2695.56   132.1 2694.76  138.99 2695.57
   144.2 2697.42   148.2 2697.75   188.3 2696.08   196.3 2698.02   204.4 2699.05
   220.4 2699.06   256.5 2700.32   264.6 2702.35   275.9 2703.32   283.3 2703.41
   292.7 2704.67   304.7 2706.94   328.8 2712.56   336.8 2713.91   362.8  2716.1
#Mann= 3 ,-1,0
       0      .1       0  127.56    .045       0  138.99      .1       0
Bank Sta=127.56,138.99
XS Rating Curve= 0 ,0
Exp/Cntr=0.3,0.1

Type RM Length L Ch R = 1 ,2564    ,277,277.8,277.8
XS GIS Cut Line= 2
2355939.80265725689782.7957923112356144.76635576690154.001860171
#Sta/Elev= 30
       0 2750.08    16.4 2742.54    37.4 2735.81    48.4 2730.46    75.8 2720.62
    87.4 2713.27   108.3 2696.13  116.03 2691.76   121.5 2690.99   127.92691.762
   139.8 2693.08   155.1 2692.38   163.9 2694.72   169.8 2695.44   176.4  2695.5
   190.1 2693.95   199.4 2695.78     222 2695.33   235.8 2696.02   258.1 2695.46
     286 2696.15   295.2 2697.61   302.3 2699.85   308.9 2702.03   321.4 2707.91
   327.1 2709.68   364.1 2715.53   399.4 2719.28   409.4 2720.88     424 2724.92
#Mann= 3 ,-1,0
       0      .1       0  116.03    .045       0   127.9      .1       0
Bank Sta=116.03,127.9
XS Rating Curve= 0 ,0
Exp/Cntr(USF)=0,0
Exp/Cntr=0.3,0.1

Type RM Length L Ch R = 1 ,2287    ,184.2,185.4,186.4
XS GIS Cut Line= 2
2355696.24164061689893.6046132382355870.62444602 690229.52096472
#Sta/Elev= 30
       0 2730.28    20.4 2722.76    51.9 2712.68    71.6 2709.99    76.1 2708.69
    85.2 2704.27    98.7 2701.36   103.2 2699.43   116.7    2691   121.2 2688.87
   125.7 2687.75   139.2 2686.58   150.9 2684.13   161.8 2683.82   166.92684.123
   177.6 2685.67   192.5 2684.09   197.8 2684.31   206.8 2687.12   211.3 2687.72
   238.4 2687.13   245.9  2687.9   254.8 2691.69   269.6  2701.6   274.4 2703.48
   305.2 2708.43   331.9 2714.67   346.5 2719.56   355.6 2721.36   378.5 2729.96
#Mann= 3 ,-1,0
       0      .1       0   150.9    .045       0   166.9      .1       0
Bank Sta=150.9,166.9
XS Rating Curve= 0 ,0
Exp/Cntr(USF)=0,0
Exp/Cntr=0.3,0.1

Type RM Length L Ch R = 1 ,2101    ,248.7,249,247.7
XS GIS Cut Line= 2
2355544.04056473689940.1044033192355658.62395297690266.822448068
#Sta/Elev= 30
       0  2741.3     7.2 2738.02    22.9 2732.71    47.8 2719.78    64.7 2709.46
    77.4  2704.5    81.7 2701.16    90.2 2692.74    98.6 2685.55   104.5 2682.06
   113.9 2680.62   132.8 2681.91   170.7 2681.86   174.9 2681.55   182.72679.321
   192.4 2678.85  197.98 2679.33   204.6 2680.97   213.1 2680.52   217.5 2681.04
   221.6 2683.44     230 2690.07   242.1 2693.95   285.1 2700.33   289.7 2701.74
   306.3 2709.37   314.8 2711.99   323.3 2716.11     336 2719.13   346.2 2723.09
#Mann= 3 ,-1,0
       0      .1       0   182.7    .045       0  197.98      .1       0
#XS Ineff= 2 , 0
          142.02 2684.42
Permanent Ineff=
       F       F
Bank Sta=182.7,197.98
XS Rating Curve= 0 ,0
Exp/Cntr(USF)=0,0
Exp/Cntr=0.3,0.1

Type RM Length L Ch R = 1 ,1852    ,345.8,343.2,336.1
XS GIS Cut Line= 2
2355288.09791839690007.4238661862355447.72618789690330.648463107
#Sta/Elev= 30
       0 2730.18     6.4 2727.99    19.8 2721.95    31.2 2720.13    37.6  2718.4
    43.2 2715.53    55.5 2710.73    95.6 2700.31   102.9 2697.91   113.5 2693.68
   126.9 2685.95   135.7 2682.19   158.1 2679.21   171.5 2675.07   180.12673.773
   189.3  2673.3  191.98 2673.77   211.6 2676.13     225 2675.81   229.5 2674.94
   238.4 2675.62   256.2 2674.87     283 2674.85   289.2 2675.32     294 2677.03
   320.9 2691.97   327.6 2694.48   338.8 2696.72   354.4 2701.95   360.5 2704.64
#Mann= 3 ,-1,0
       0      .1       0   180.1    .045       0  191.98      .1       0
Bank Sta=180.1,191.98
XS Rating Curve= 0 ,0
Exp/Cntr(USF)=0,0
Exp/Cntr=0.3,0.1

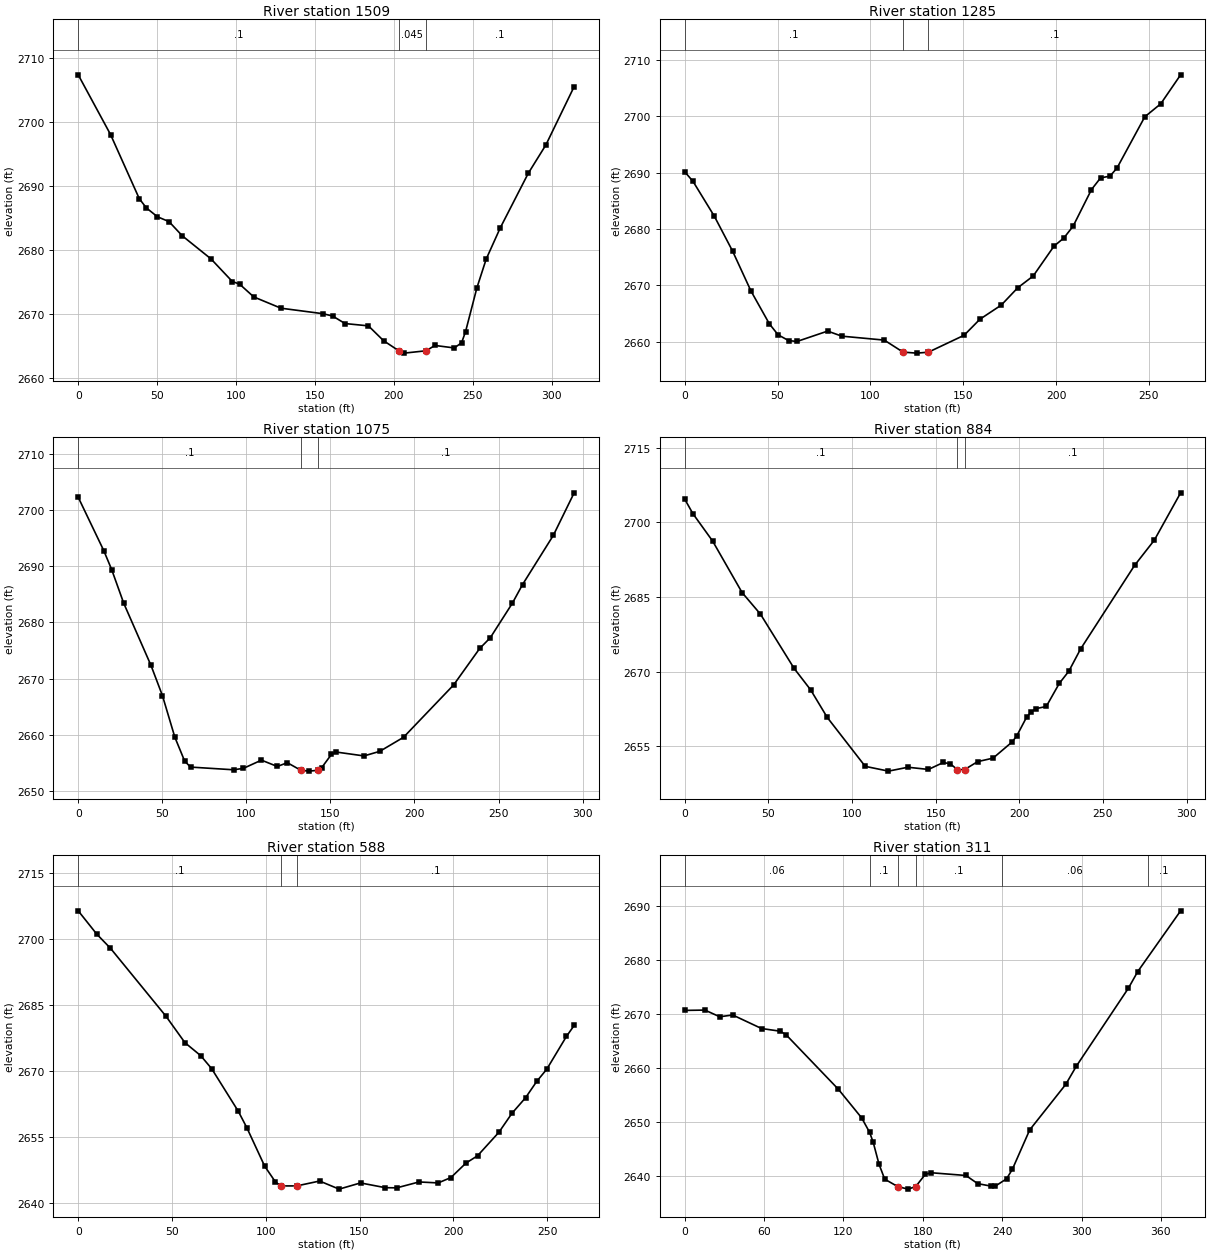
Type RM Length L Ch R = 1 ,1509    ,225.1,224.3,228.8
XS GIS Cut Line= 2
2354962.09148118690305.5033373132355239.09030734690453.637492173
#Sta/Elev= 30
       0 2707.31    20.5 2697.97    38.7 2687.95    43.2 2686.51    50.2 2685.13
    57.5 2684.38    65.9 2682.16    84.1 2678.55    97.6 2675.02   102.2 2674.61
   111.2 2672.61   128.4 2670.85     155 2669.99   161.1 2669.63     169 2668.45
   183.8 2668.09   193.4 2665.77   202.9 2664.22   206.5 2663.83   220.4  2664.2
   225.9 2665.03   238.2 2664.64   242.8 2665.45   245.3 2667.17   252.5 2674.03
   258.4 2678.53   267.3  2683.4     285 2691.91   296.2 2696.36   314.1 2705.47
#Mann= 3 ,-1,0
       0      .1       0   202.9    .045       0   220.4      .1       0
Bank Sta=202.9,220.4
XS Rating Curve= 0 ,0
Exp/Cntr(USF)=0,0
Exp/Cntr=0.3,0.1

Type RM Length L Ch R = 1 ,1285    ,209.7,209.7,209.1
XS GIS Cut Line= 2
2354875.37880516 690471.702633012355090.95615248690629.471529649
#Sta/Elev= 30
       0 2690.14     4.5 2688.42      16 2682.23    25.8 2676.06    35.7 2668.98
    45.6 2663.16    50.3 2661.21      56 2660.18    60.5 2660.03      77 2661.87
    84.6 2660.97   107.5 2660.27   117.6 2658.14   124.9 2657.96   131.2 2658.12
   150.5 2661.13     159 2663.97   170.5 2666.48   179.4 2669.56   187.7 2671.64
   198.9 2676.94   204.2 2678.38   209.2 2680.48   219.1 2686.98     224 2689.05
     229 2689.35   232.8 2690.77   247.8 2699.88   256.4 2702.19   267.1 2707.33
#Mann= 3 ,-1,0
       0      .1       0   117.6    .045       0   131.2      .1       0
Bank Sta=117.6,131.2
XS Rating Curve= 0 ,0
Exp/Cntr(USF)=0,0
Exp/Cntr=0.3,0.1

Type RM Length L Ch R = 1 ,1075    ,189.5,190.9,190.8
XS GIS Cut Line= 2
2354727.24116265690635.0047878462354978.71952414690789.195900001
#Sta/Elev= 30
       0 2702.32    15.2 2692.81    19.9 2689.43    27.1 2683.41    43.3 2672.34
    50.1 2666.96    57.5 2659.53    63.3  2655.3    66.8 2654.22    92.4 2653.74
    98.2 2653.99     109 2655.46   118.4 2654.33   124.4    2655   132.5 2653.64
   137.2  2653.5   142.42653.638   144.8 2654.11   150.6 2656.47   153.5  2656.9
     170 2656.21   179.4 2657.03   193.5 2659.53   223.3 2668.86   238.8 2675.36
   245.1 2677.27   258.2 2683.41   264.3 2686.76   282.6 2695.52     295 2703.11
#Mann= 3 ,-1,0
       0      .1       0   132.5    .045       0   142.4      .1       0
Bank Sta=132.5,142.4
XS Rating Curve= 0 ,0
Exp/Cntr(USF)=0,0
Exp/Cntr=0.3,0.1

Type RM Length L Ch R = 1 ,884     ,296.5,296.1,294.4
XS GIS Cut Line= 2
2354611.06456301690737.8135721032354827.84625305690939.875517757
#Sta/Elev= 30
       0 2704.67     4.9 2701.74    16.7 2696.23    34.3 2685.89    45.3 2681.54
    65.4 2670.65    75.3 2666.33    85.2  2660.8   107.9 2650.97   121.8 2650.01
   133.4 2650.79   145.7 2650.35   154.6 2651.75   158.8 2651.46     1632650.314
   167.3 2650.32   175.1 2651.92   184.3 2652.62   195.6 2655.84   198.4 2657.05
   204.4 2660.88   206.9  2661.8   209.8 2662.55   216.1    2663   223.9 2667.64
   229.6 2670.09   236.6 2674.54   268.9 2691.35   280.7 2696.42   296.4 2705.92
#Mann= 3 ,-1,0
       0      .1       0     163    .045       0   167.3      .1       0
Bank Sta=163,167.3
XS Rating Curve= 0 ,0
Exp/Cntr(USF)=0,0
Exp/Cntr=0.3,0.1

Type RM Length L Ch R = 1 ,588     ,277.6,276.7,273
XS GIS Cut Line= 2
2354406.40836486690902.7290824662354607.29452526691074.698114049
#Sta/Elev= 30
       0 2706.49     9.9 2701.19    17.2 2697.98    46.8 2682.53    56.9 2676.53
    65.3 2673.58    71.1 2670.65    85.3 2660.97    89.9 2657.21    99.4 2648.47
   105.1 2644.91   107.92643.978   116.5 2643.98   128.7 2645.09   139.1 2643.25
   150.5 2644.66   163.7 2643.58   169.8 2643.54   181.7 2644.88   191.9 2644.66
   198.7 2645.88   206.7 2649.16   212.9 2650.83   224.3 2656.18   231.3 2660.51
   238.5 2664.02   244.5 2667.76   249.8  2670.5   260.3 2677.96   264.4 2680.44
#Mann= 3 ,-1,0
       0      .1       0   107.9    .045       0   116.5      .1       0
Bank Sta=107.9,116.5
XS Rating Curve= 0 ,0
Exp/Cntr(USF)=0,0
Exp/Cntr=0.3,0.1

Type RM Length L Ch R = 1 ,311     ,152.1,157.5,156.5
XS GIS Cut Line= 2
2354166.20999678691098.3134746782354508.18385624 691251.95390429
#Sta/Elev= 30
       0 2670.72    15.3 2670.78    26.5 2669.54    36.3 2669.87    58.1 2667.36
    72.3 2666.86    76.7 2666.19   116.2 2656.09   133.8 2650.78   139.8  2648.1
   142.5 2646.27   146.9  2642.2   151.2 2639.42     161 2638.05   168.8 2637.57
   174.62638.032   181.9 2640.31   186.3 2640.61   212.6  2640.1   221.5 2638.59
   231.5 2638.13   234.6 2638.09   243.3 2639.48   247.7 2641.24   260.8 2648.55
   288.1 2657.01     296 2660.35   335.4 2674.83   342.5 2677.93   374.9 2689.19
#Mann= 6 ,-1,0
       0     .06       0     140      .1       0     161    .045       0
   174.6      .1       0     240     .06       0     350      .1       0
Bank Sta=161,174.6
XS Rating Curve= 0 ,0
Exp/Cntr(USF)=0,0
Exp/Cntr=0.3,0.1

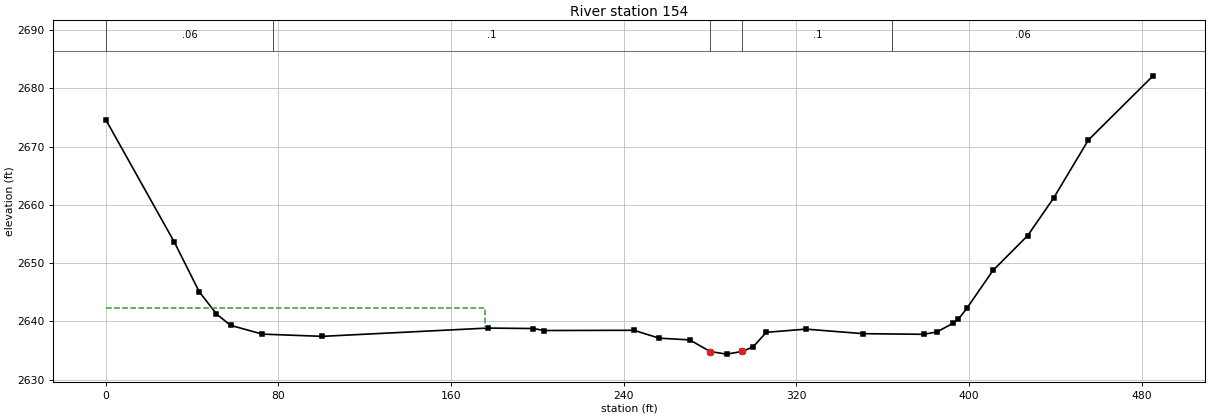
Type RM Length L Ch R = 1 ,154     ,,,
XS GIS Cut Line= 4
2354141.33021902 691086.008111342354145.51723266691143.316271558
2354355.79935254 691323.637651292354506.05403919 691310.88856736
#Sta/Elev= 30
       0 2674.62    31.8 2653.59    43.3  2645.1    51.3 2641.29    57.8 2639.34
    72.6 2637.83   100.4 2637.45   176.9 2638.87     198 2638.79   203.2 2638.45
   244.7 2638.49   256.4 2637.14   270.6 2636.84   280.12634.841   287.7  2634.4
  295.01 2634.86     300 2635.66   306.1 2638.14   324.5 2638.69   350.9 2637.91
     379  2637.8   385.2 2638.21   392.6  2639.7   395.1 2640.39   399.1  2642.3
   411.1 2648.75   427.2 2654.73   439.2 2661.16   455.3 2671.12   485.3 2682.14
#Mann= 5 ,-1,0
       0     .06       0   77.46      .1       0   280.1    .045       0
  295.01      .1       0  364.47     .06       0
#XS Ineff= 2 , 0
          175.61 2642.27
Permanent Ineff=
       F       F
Bank Sta=280.1,295.01
XS Rating Curve= 0 ,0
Exp/Cntr(USF)=0,0
Exp/Cntr=0.3,0.1
LCMann Table=0

Chan Stop Cuts=-1
Use User Specified Reach Order=0
Composite Channel Slope=5